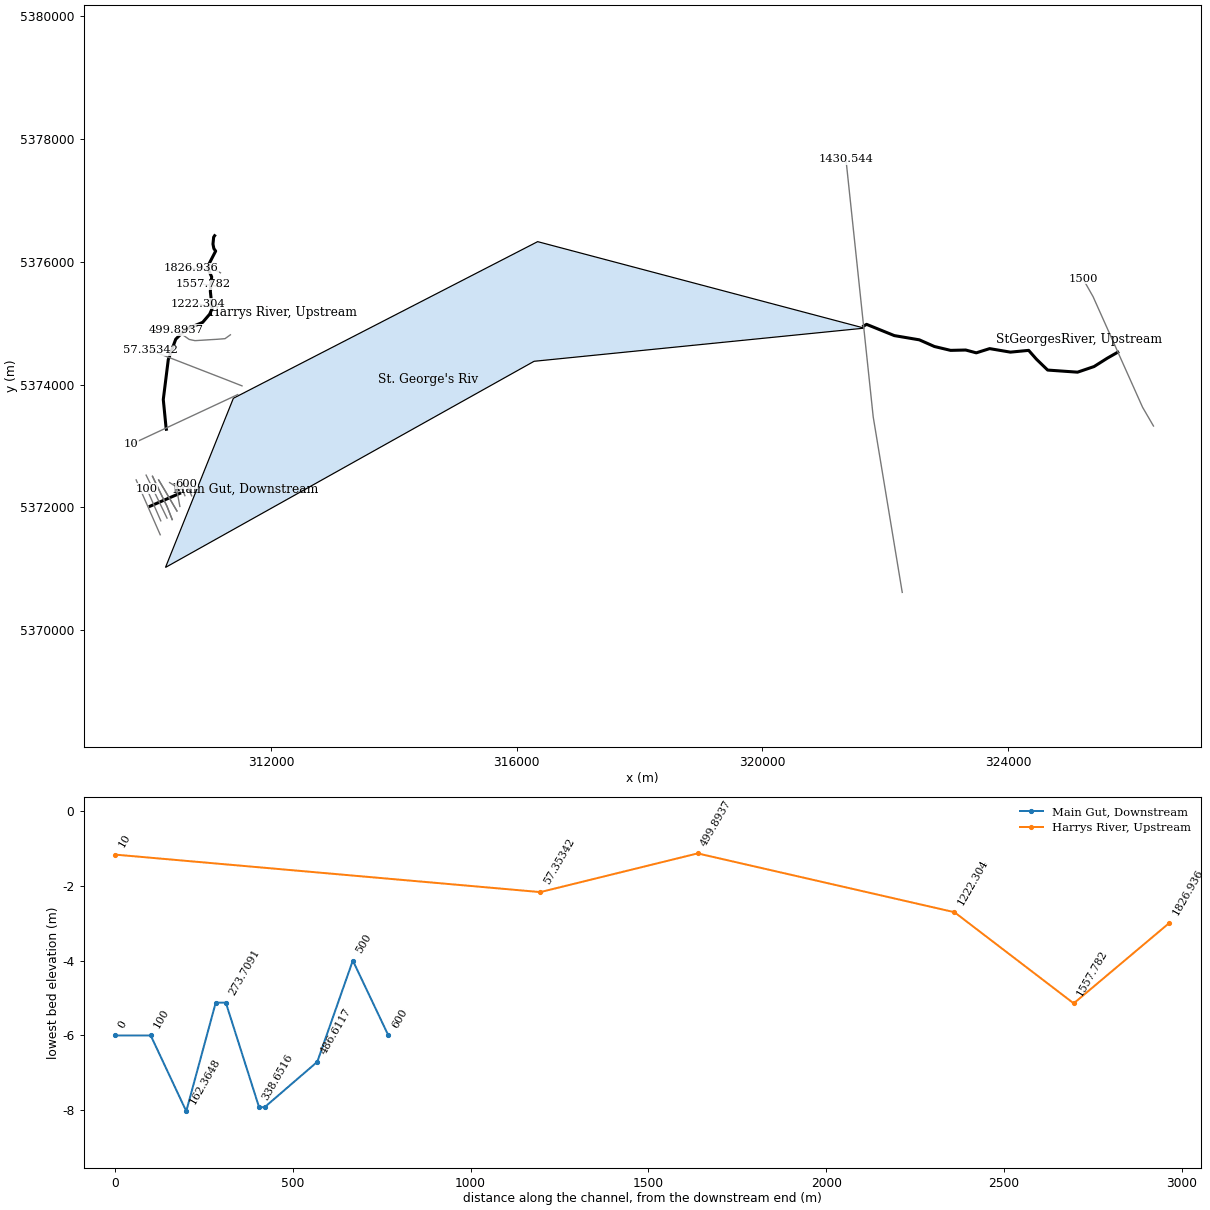
HEC-RAS study StephenvilleCrossi.prj: Stephenville Crossing Model

--- StephenvilleCrossi.g11 (geometry) --- (continued)

River Reach=StGeorgesRiver  ,Upstream
Reach XY= 30
325787.2534244415374526.76314809 325713.031005685374484.35033736
325619.7506830125374431.04729584325402.1528836835374293.61710679
325133.0187634585374201.99698076 325038.34314068 5374208.6799659
 324975.003180815374213.15102188324945.3197112915374215.24632562
324646.2868439065374236.35452802324463.0465918395374413.86852221
324337.0689185425374557.02496914324039.3035089345374528.39367975
323923.632506475 5374547.9989344323752.5187325245374577.00126898
323739.6213088695374579.18727298323701.4542941835374585.65625852
323586.7594367325374549.43682986323483.8564948555374516.94116399
323323.4422921215374559.71828473323312.0687585445374562.75122701
323311.976096985 5374562.7490721323065.8396698275374557.02496914
322802.4318074815374620.01380579322556.2027187655374728.81270545
322149.6384094935374797.52779998 321929.610017565374886.65322455
321816.8070555255374932.34556361  321697.26403725374980.76805204
321662.5232427555374960.63418254 321650.32833285  5374954.116857
Reach Downstream Storage Area=St. George's Riv

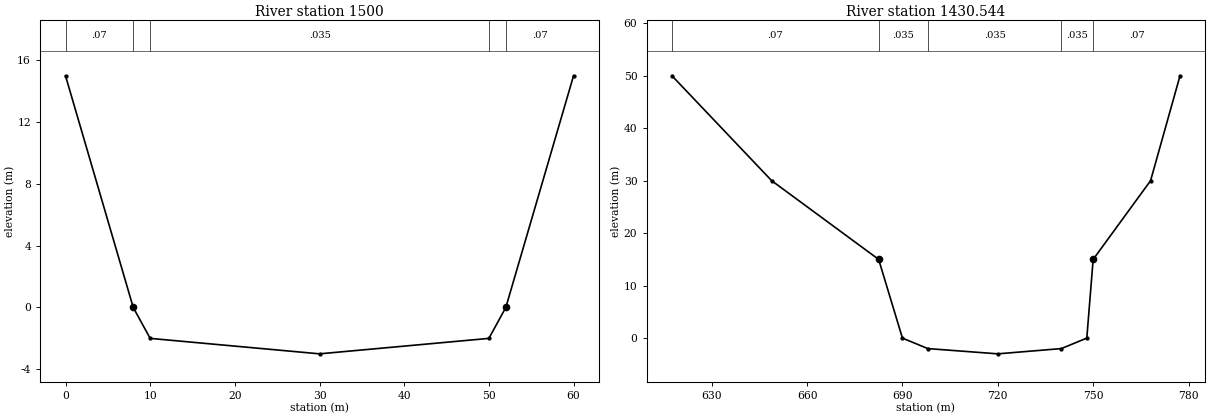
Type RM Length L Ch R = 1 ,1500    ,100,100,100
XS GIS Cut Line= 4
   326369.870385  5373325.016413   326192.025945  5373630.686544
   325386.168327  5375431.361498   325219.439165  5375725.916351
#Sta/Elev= 7
       0      15       8       0      10      -2      30      -3      50      -2
      52       0      60      15
#Mann= 5 ,-1 , 0
       0     .07       0       8    .035       0      10    .035       0
      50    .035       0      52     .07       0
Bank Sta=8,52
XS Rating Curve= 0 ,0
Exp/Cntr(USF)=0.3,0.1
Exp/Cntr=0.3,0.1

Type RM Length L Ch R = 1 ,1430.544,100,100,100
XS GIS Cut Line= 3
   322278.213237  5370615.667524   321805.350807  5373474.995469
   321361.588791  5377668.484769
#Sta/Elev= 11
 617.502      50 648.871      30 682.522      15     690       0     698      -2
     720      -3     740      -2     748       0     750      15 768.057      30
 777.323      50
#Mann= 5 ,-1 , 0
 617.502     .07       0 682.522    .035       0     698    .035       0
     740    .035       0     750     .07       0
Bank Sta=682.522,750
XS Rating Curve= 0 ,0
Exp/Cntr(USF)=0.3,0.1
Exp/Cntr=0.3,0.1

River Reach=Main Gut        ,Downstream
Reach XY= 30
310510.5817172655372227.10651686310488.0938673985372217.65574792
310484.6737034375372216.17485218310437.487900597  5372195.743886
310431.2975929415372193.06354661310427.4594280835372191.40166079
310380.8832912755372171.23467372310380.0799618365372170.88684035
310353.9080926095372159.55469079310353.6134072235372159.42709506
 310352.124133655372158.78225495310349.0752575595372157.46212304
310348.8060889685372157.34557581310334.028989295  5372150.947244
310309.5495486695372140.34789857310299.9381480385372136.18626119
310288.0838229865372131.05346065310277.4563096535372126.45185693
 310273.753167685372124.84843464310243.5718115135372111.78021856
310201.3244108265372093.48752961 310181.943336175372085.09572408
310162.5979054595372076.71935203310154.2463459875372073.10321287
310135.4085224495372064.94662949310121.6574832995372058.99257129
310117.2944867265372057.10343876310084.5488244845372042.92490459
310062.1738911435372033.23678913310031.049127174 5372019.7600872
Reach Upstream Storage Area=St. George's Riv

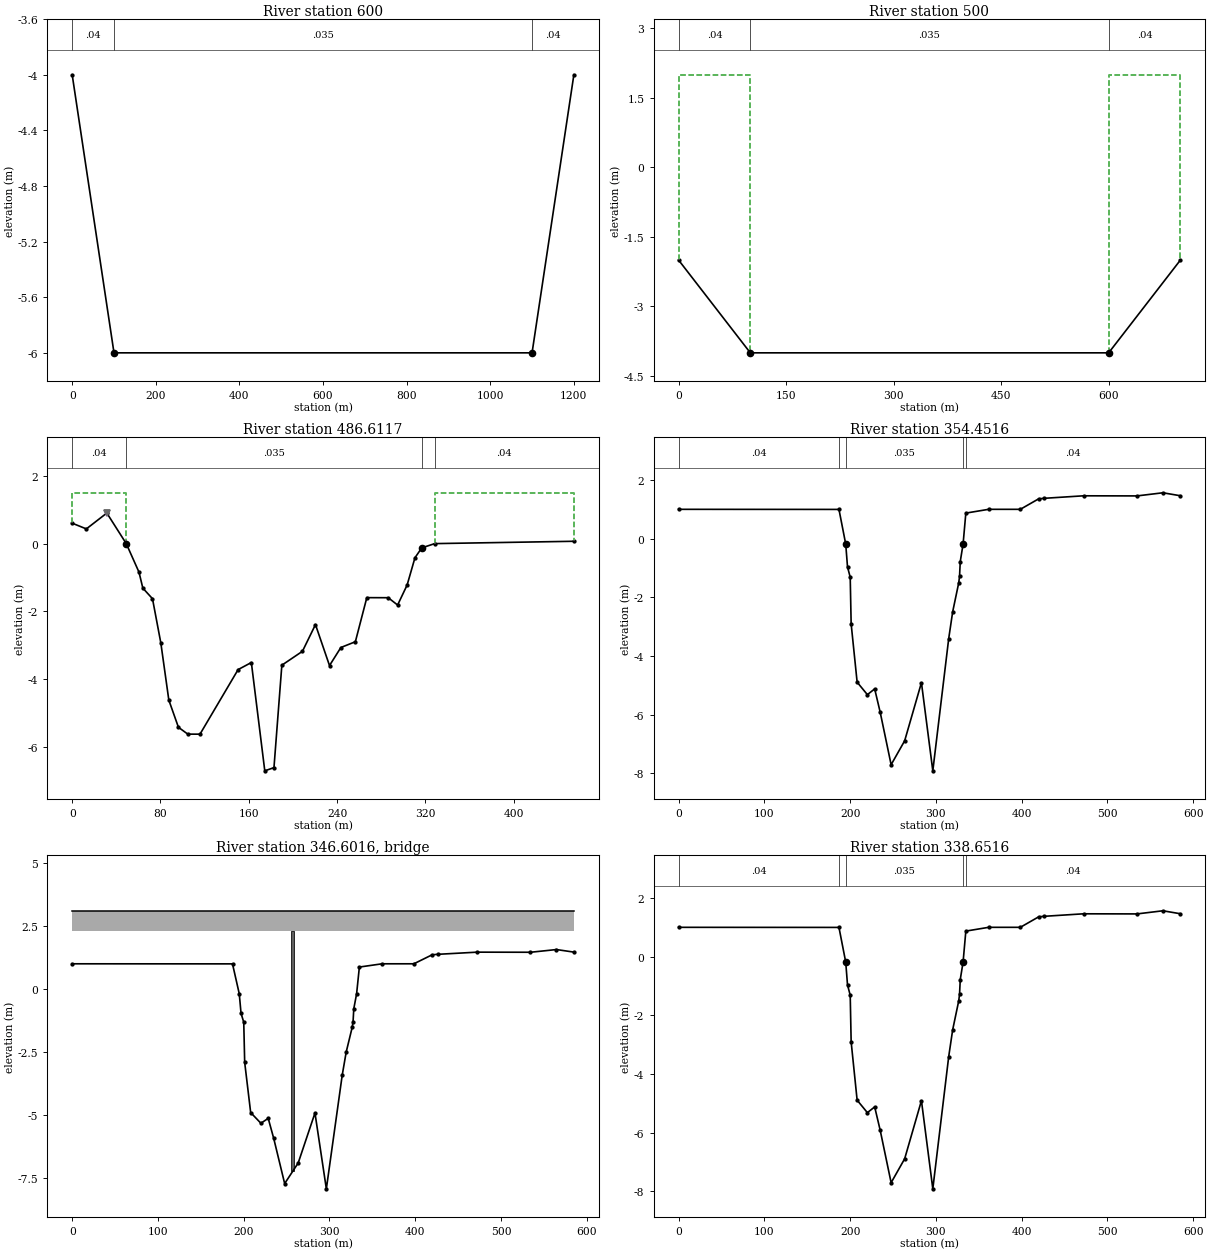
Type RM Length L Ch R = 1 ,600     ,100,100,100
XS GIS Cut Line= 2
   310706.355073  5372187.572535   310621.783578  5372388.986227
#Sta/Elev= 4
       0      -4     100      -6    1100      -6    1200      -4
#Mann= 3 ,-1 , 0
       0     .04       0     100    .035       0    1100     .04       0
#XS Ineff= 2 , 0
       0     100            1100       0
Permanent Ineff=
       T       T
Bank Sta=100,1100
XS Rating Curve= 0 ,0
Exp/Cntr(USF)=0.8,0.6
Exp/Cntr=0.8,0.6

Type RM Length L Ch R = 1 ,500     ,100,100,100
BEGIN DESCRIPTION:
Estimated Section upstream
END DESCRIPTION:
XS GIS Cut Line= 2
   310596.667415  5372191.213859   310547.587146  5372307.360334
#Sta/Elev= 4
       0      -2     100      -4     600      -4     700      -2
#Mann= 3 ,-1 , 0
       0     .04       0     100    .035       0     600     .04       0
#XS Ineff= 2 , 0
       0     100       2     600       0       2
Permanent Ineff=
       T       T
Bank Sta=100,600
XS Rating Curve= 0 ,0
Exp/Cntr(USF)=0.8,0.6
Exp/Cntr=0.8,0.6

Type RM Length L Ch R = 1 ,486.6117,147.96,147.96,147.96
BEGIN DESCRIPTION:
Section 6
END DESCRIPTION:
XS GIS Cut Line= 4
310514.2961269785372015.28637233 310508.565600555372046.04946931
310454.3933497185372338.29863764310346.9874727885372404.35154608
#Sta/Elev= 30
       0    .603  12.836    .434  31.388    .902  49.001       0  60.532   -.842
  64.028  -1.314  72.763  -1.625  80.304  -2.926  87.577  -4.617  96.272  -5.419
 104.761  -5.621 115.814  -5.622 150.353  -3.717 162.352  -3.508 174.527  -6.704
 182.848  -6.609 189.987  -3.587 208.651  -3.177 220.454  -2.389 233.177  -3.598
 243.472  -3.065  256.61  -2.895 266.985  -1.594 286.383  -1.596 294.898  -1.812
 303.519  -1.221 310.606   -.417 316.758   -.126  328.52       0 454.611    .069
#Mann= 4 ,-1 , 0
       0     .04       0  49.001    .035       0 316.758     .04       0
  328.52     .04       0
Levee=-1,31.22,0.9,0,,,Levee 1,
#XS Ineff= 2 , 0
       0  49.001     1.5  328.52       0     1.5
Permanent Ineff=
       T       T
Bank Sta=49.001,316.758
XS Rating Curve= 0 ,0
Exp/Cntr(USF)=0.5,0.3
Exp/Cntr=0.5,0.3

Type RM Length L Ch R = 1 ,354.4516,15.8,15.8,15.8
BEGIN DESCRIPTION:
Section 7 - copy U/S of bridge
END DESCRIPTION:
XS GIS Cut Line= 4
310466.4877987325371941.93724135310382.971055656 5372084.0646572
310283.1733203435372254.44550834310169.4688726595372445.91687684
#Sta/Elev= 29
       0       1 186.937    .997 194.821   -.187 196.898   -.963 200.052  -1.314
 201.145  -2.905  208.12  -4.892 220.059  -5.317 228.574  -5.121 234.984  -5.914
 247.758  -7.705 263.547  -6.889 283.103  -4.909  296.37  -7.914 314.898  -3.407
 319.526  -2.493  326.55  -1.511 327.532  -1.287 328.368    -.78 331.663   -.187
  334.87    .871  361.42       1 398.414       1 419.763   1.357 425.987   1.375
 472.202   1.461 534.418   1.457 564.695   1.564 584.994   1.463
#Mann= 5 ,-1 , 0
       0     .04       0 186.937     .04       0 194.821    .035       0
 331.663     .04       0  334.87     .04       0
Bank Sta=194.821,331.663
XS Rating Curve= 0 ,0
Exp/Cntr(USF)=0.5,0.3
Exp/Cntr=0.5,0.3

Type RM Length L Ch R = 3 ,346.6016,,,
BEGIN DESCRIPTION:
Railway Bridge
END DESCRIPTION:
Bridge Culvert--1,0,-1,-1, 0
Deck Dist Width WeirC Skew NumUp NumDn MinLoCord MaxHiCord MaxSubmerge Is_Ogee
5.3,5.3,1.4,0, 2, 2, , , 0.98, 0, 0,0,,
       0 584.994
     3.1     3.1
     2.3     2.3
       0 584.994
     3.1     3.1
     2.3     2.3
Pier Skew, UpSta & Num, DnSta & Num=  ,257.2682, 2 ,257.2682, 2 , 0 , 0 , 0 ,,
     3.7     3.7
     -10     2.3
     3.7     3.7
     -10     2.3
Abutment Skew #Up #Dn= , 3 , 3
       0 187.069 187.069
     2.3     2.3      -6
       0 187.069 187.069
     2.3     2.3      -6
Abutment Skew #Up #Dn= , 3 , 3
 327.431 327.431 584.994
      -6     2.3     2.3
 327.431 327.431 584.994
      -6     2.3     2.3
BR Coef=-1 , 0 , 0 ,, 0 ,,,0.8,-1,,0,
WSPro=,,,, 1 ,,,, 0 ,,,, 0 ,,,,-1 ,-1 ,-1 , 0 , 0 , 0 , 0 , 0
BC Design=,, 0 ,, 0 ,,,,,,
BC HTab HWMax=4
BC Use User HTab Curves=0
BC User HTab FreeFlow(D)= 0

Type RM Length L Ch R = 1 ,338.6516,93.44,93.44,93.44
BEGIN DESCRIPTION:
Section 7
END DESCRIPTION:
XS GIS Cut Line= 4
310466.4877987325371941.93724135310382.971055656 5372084.0646572
310283.1733203435372254.44550834310169.4688726595372445.91687684
#Sta/Elev= 29
       0       1 186.937    .997 194.821   -.187 196.898   -.963 200.052  -1.314
 201.145  -2.905  208.12  -4.892 220.059  -5.317 228.574  -5.121 234.984  -5.914
 247.758  -7.705 263.547  -6.889 283.103  -4.909  296.37  -7.914 314.898  -3.407
 319.526  -2.493  326.55  -1.511 327.532  -1.287 328.368    -.78 331.663   -.187
  334.87    .871  361.42       1 398.414       1 419.763   1.357 425.987   1.375
 472.202   1.461 534.418   1.457 564.695   1.564 584.994   1.463
#Mann= 5 ,-1 , 0
       0     .04       0 186.937     .04       0 194.821    .035       0
 331.663     .04       0  334.87     .04       0
Bank Sta=194.821,331.663
XS Rating Curve= 0 ,0
Exp/Cntr(USF)=0.5,0.3
Exp/Cntr=0.5,0.3

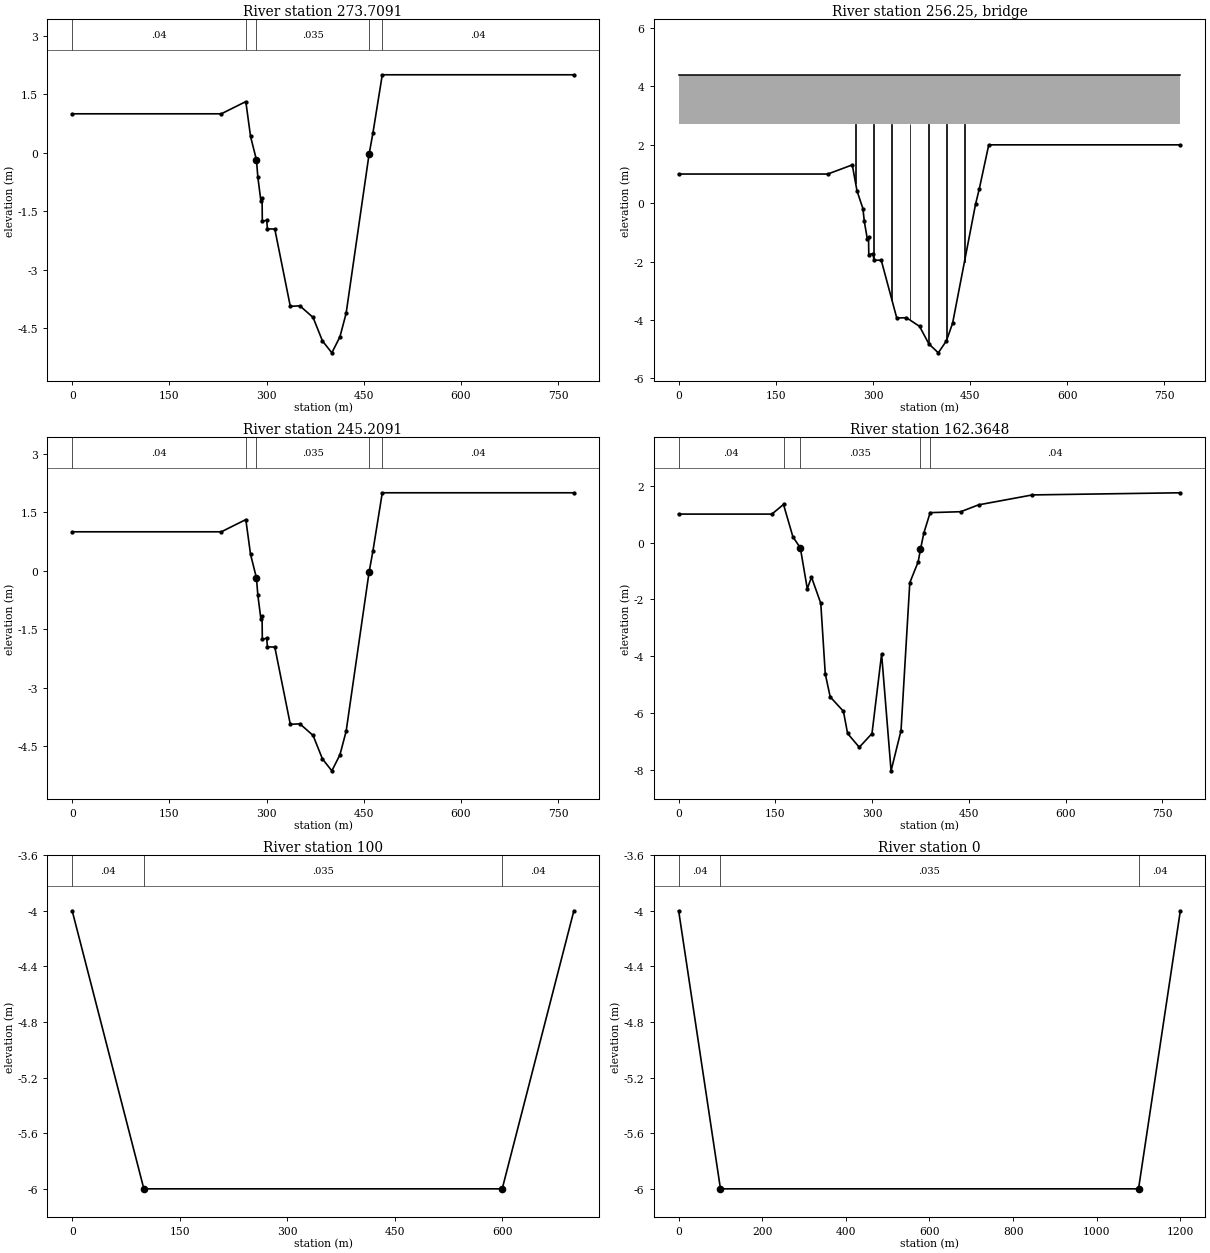
Type RM Length L Ch R = 1 ,273.7091,28.5,28.5,28.5
BEGIN DESCRIPTION:
Section 8 - copy for U/S of 490 Bridge
END DESCRIPTION:
XS GIS Cut Line= 4
310389.539017995 5371801.8106011310305.3311073265372016.10601793
310195.0715964365372242.36503149310068.802837218 5372506.3164981
#Sta/Elev= 23
       0       1 230.247       1 268.055   1.313 275.391    .419   284.5   -.183
 286.646   -.624 291.323  -1.231  293.16  -1.169 293.548  -1.758 300.299  -1.724
 301.412  -1.948 312.807  -1.954 336.742  -3.933 351.593  -3.921 371.911  -4.218
  386.38   -4.82 400.885  -5.125 413.373  -4.714 422.927  -4.113 458.317    -.04
 464.199    .497 478.755       2  774.54       2
#Mann= 5 ,-1 , 0
       0     .04       0 268.055     .04       0   284.5    .035       0
 458.317     .04       0 478.755     .04       0
Bank Sta=284.5,458.317
XS Rating Curve= 0 ,0
Exp/Cntr(USF)=0.5,0.3
Exp/Cntr=0.5,0.3

Type RM Length L Ch R = 3 ,256.25  ,,,
BEGIN DESCRIPTION:
Route 490 Bridge
END DESCRIPTION:
Bridge Culvert--1,0,-1,-1, 0
Deck Dist Width WeirC Skew NumUp NumDn MinLoCord MaxHiCord MaxSubmerge Is_Ogee
11.7,11.7,1.4,0, 2, 2, , , 0.98, 0, 0,0,,
       0  774.54
     4.4     4.4
     2.7     2.7
       0  774.54
     4.4     4.4
     2.7     2.7
Pier Skew, UpSta & Num, DnSta & Num=  ,273.1152, 2 ,273.1152, 2 , 0 , 0 , 0 ,,
     1.2     1.2
     -10     2.7
     1.2     1.2
     -10     2.7
Pier Skew, UpSta & Num, DnSta & Num=  ,301.1349, 2 ,301.1349, 2 , 0 , 0 , 0 ,,
     1.2     1.2
     -10     2.7
     1.2     1.2
     -10     2.7
Pier Skew, UpSta & Num, DnSta & Num=  ,329.1781, 2 ,329.1781, 2 , 0 , 0 , 0 ,,
     1.2     1.2
     -10     2.7
     1.2     1.2
     -10     2.7
Pier Skew, UpSta & Num, DnSta & Num=  ,357.2134, 2 ,357.2134, 2 , 0 , 0 , 0 ,,
     1.2     1.2
     -10     2.7
     1.2     1.2
     -10     2.7
Pier Skew, UpSta & Num, DnSta & Num=  ,385.2242, 2 ,385.2242, 2 , 0 , 0 , 0 ,,
     1.2     1.2
     -10     2.7
     1.2     1.2
     -10     2.7
Pier Skew, UpSta & Num, DnSta & Num=  ,413.254, 2 ,413.254, 2 , 0 , 0 , 0 ,,
     1.2     1.2
     -10     2.7
     1.2     1.2
     -10     2.7
Pier Skew, UpSta & Num, DnSta & Num=  ,441.2927, 2 ,441.2927, 2 , 0 , 0 , 0 ,,
     1.2     1.2
     -10     2.7
     1.2     1.2
     -10     2.7
Abutment Skew #Up #Dn= , 3 , 3
       0 241.424 268.055
     2.7    3.02   1.313
       0 241.424 268.055
     2.7    3.02   1.313
Abutment Skew #Up #Dn= , 3 , 3
 464.199 467.761  774.54
    .497     2.7     2.7
 464.199 467.761  774.54
    .497     2.7     2.7
BR Coef=-1 , 0 , 0 ,, 0 ,,,0.8,-1,,0,
WSPro=,,,, 1 ,,,, 0 ,,,, 0 ,,,,-1 ,-1 ,-1 , 0 , 0 , 0 , 0 , 0
BC Design=,, 0 ,, 0 ,,,,,,
BC HTab HWMax=4
BC Use User HTab Curves=0
BC User HTab FreeFlow(D)= 0

Type RM Length L Ch R = 1 ,245.2091,82.84,82.84,82.84
BEGIN DESCRIPTION:
Section 8
END DESCRIPTION:
XS GIS Cut Line= 4
310389.539017995 5371801.8106011310305.3311073265372016.10601793
310195.0715964365372242.36503149310068.802837218 5372506.3164981
#Sta/Elev= 23
       0       1 230.247       1 268.055   1.313 275.391    .419   284.5   -.183
 286.646   -.624 291.323  -1.231  293.16  -1.169 293.548  -1.758 300.299  -1.724
 301.412  -1.948 312.807  -1.954 336.742  -3.933 351.593  -3.921 371.911  -4.218
  386.38   -4.82 400.885  -5.125 413.373  -4.714 422.927  -4.113 458.317    -.04
 464.199    .497 478.755       2  774.54       2
#Mann= 5 ,-1 , 0
       0     .04       0 268.055     .04       0   284.5    .035       0
 458.317     .04       0 478.755     .04       0
Bank Sta=284.5,458.317
XS Rating Curve= 0 ,0
Exp/Cntr(USF)=0.5,0.3
Exp/Cntr=0.5,0.3

Type RM Length L Ch R = 1 ,162.3648,100,100,100
BEGIN DESCRIPTION:
Section 9
END DESCRIPTION:
XS GIS Cut Line= 3
  310305.2056559  5371825.684206  310110.5251044  5372227.912267
  309964.8895103  5372525.150788
#Sta/Elev= 26
       0       1 144.565       1 162.574   1.338 177.164      .2  188.67   -.187
 199.427  -1.622 205.977  -1.216 220.369  -2.135 227.317  -4.615 234.956  -5.423
 255.481   -5.93 261.938   -6.71 280.059  -7.194 299.768  -6.713 314.677  -3.918
 329.357  -8.023 344.783  -6.608  358.39  -1.411 371.312   -.682 374.983   -.235
  380.23    .339 389.954   1.051  437.42   1.084 464.933   1.324 548.563   1.674
 777.864   1.749
#Mann= 5 ,-1 , 0
       0     .04       0 162.574     .04       0  188.67    .035       0
 374.983     .04       0 389.954     .04       0
Bank Sta=188.67,374.983
XS Rating Curve= 0 ,0
Exp/Cntr(USF)=0.8,0.6
Exp/Cntr=0.8,0.6

Type RM Length L Ch R = 1 ,100     ,100,100,100
BEGIN DESCRIPTION:
Estimated Section downstream
END DESCRIPTION:
XS GIS Cut Line= 2
   310203.415169  5371781.245574   309976.405891  5372302.356716
#Sta/Elev= 4
       0      -4     100      -6     600      -6     700      -4
#Mann= 3 ,-1 , 0
       0     .04       0     100    .035       0     600     .04       0
#XS Ineff= 2 , 0
       0     100       2     600       0       2
Permanent Ineff=
       T       T
Bank Sta=100,600
XS Rating Curve= 0 ,0
Exp/Cntr(USF)=0.8,0.6
Exp/Cntr=0.8,0.6

Type RM Length L Ch R = 1 ,0       ,100,100,100
BEGIN DESCRIPTION:
Estimated Section Downstream
END DESCRIPTION:
XS GIS Cut Line= 2
   310194.361164  5371554.165167   309802.384992  5372448.001653
#Sta/Elev= 4
       0      -4     100      -6    1100      -6    1200      -4
#Mann= 3 ,-1 , 0
       0     .04       0     100    .035       0    1100     .04       0
#XS Ineff= 2 , 0
       0     100       2    1100       0       2
Permanent Ineff=
       T       T
Bank Sta=100,1100
XS Rating Curve= 0 ,0
Exp/Cntr(USF)=0.8,0.6
Exp/Cntr=0.8,0.6

River Reach=Harrys River    ,Upstream
Reach XY= 30
311080.3628410195376424.45970993311064.4134917375376400.53568601
311053.4662441275376287.41412739311068.0625742715376214.43247667
311097.2552345595376174.29256877310987.7827584785375962.64578168
310972.2741577025375885.55891311311032.4840195435375754.19194181
311010.5895243265375518.82611823 311040.694455255375239.67130423
310999.6422767215375146.61969956310934.4361964385375070.54593924
 310901.950170545375032.64557568310888.0947963415375016.48097246
310884.6961768365375012.51591636 310881.492430975375011.21538587
  310875.49354565375008.78019477310863.8712281065375004.06222431
310796.8781706955374976.86702278310790.0924698285374974.11243135
310776.2632505525374968.49858985310753.3194352565374959.18476385
310750.7173785395374958.12848339310711.7833966425374942.32359966
310608.2781747315374900.30662838310446.8062725125374738.83472616
310325.7259612385374407.60708308310244.3470141495373756.88890806
310289.9565764775373293.77642904310294.0998700515373272.58930118
Reach Downstream Storage Area=St. George's Riv

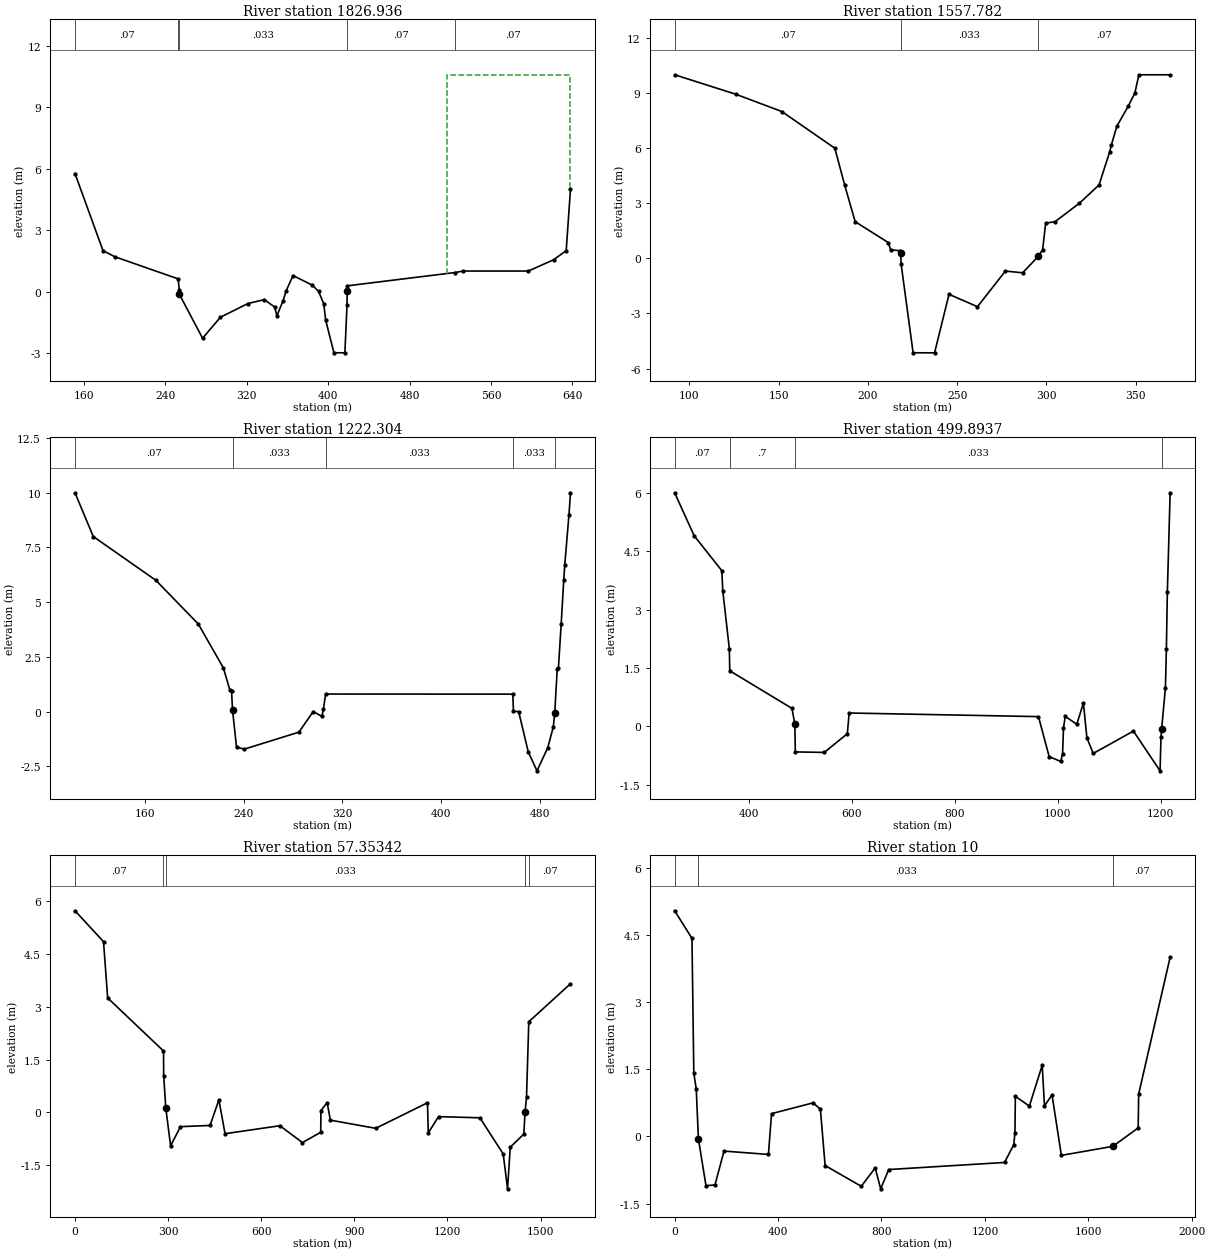
Type RM Length L Ch R = 1 ,1826.936,269.15,269.15,268.98
BEGIN DESCRIPTION:
Section 17
END DESCRIPTION:
XS GIS Cut Line= 6
311175.3780150695375820.18199221311090.6146760245375864.62074659
311085.3189746515375864.99562297310918.8165031125375877.32453082
310725.2721321375375890.72846323310700.7229627115375892.42861811
#Sta/Elev= 30
 151.432    5.76 178.891       2 190.395   1.701 252.726    .618 253.869    .076
 253.982   -.139 276.719  -2.282  294.22  -1.257  321.27   -.586 337.282   -.396
 347.428   -.755 349.755   -1.18 355.661   -.464 358.742    .026  365.53    .779
 384.439    .313  390.65    .003 395.692   -.594 397.575  -1.391 405.703  -2.989
 416.469  -2.994 418.574   -.641 418.671    .033  418.87    .279 524.664    .928
 532.727       1 596.608       1 621.578   1.554 633.822       2 638.021       5
#Mann= 5 ,-1 , 0
 151.432     .07       0 252.726     .07       0 253.982    .033       0
 418.671     .07       0 524.664     .07       0
#XS Ineff= 2 , 0
       0                 516.653       0  10.584
Permanent Ineff=
       F       F
Bank Sta=253.982,418.671
XS Rating Curve= 0 ,0
Exp/Cntr(USF)=0.3,0.1
Exp/Cntr=0.3,0.1

Type RM Length L Ch R = 1 ,1557.782,335.48,335.48,359.99
BEGIN DESCRIPTION:
Section 16
END DESCRIPTION:
XS GIS Cut Line= 4
311170.3958454965375593.84575445 311052.034291985375611.30209083
310963.677754743  5375624.822887310895.7669610995375633.83162726
#Sta/Elev= 30
  91.717      10 125.946   8.941 151.724       8 181.443       6 186.932       4
 192.827       2 211.359    .865 212.725    .465 217.875    .421 218.331    .306
 218.563   -.298 225.283  -5.139   237.3  -5.143 245.395  -1.956 261.346  -2.631
 276.964    -.69 286.633   -.784 295.372    .107 297.848     .48 299.523   1.919
 304.789       2 318.391       3  329.43       4 335.371   5.794 336.324   6.177
 339.445   7.207 345.715   8.276  349.47       9  351.76      10  369.25      10
#Mann= 3 , 0 , 0
  91.717     .07       0 218.331    .033       0 295.372     .07       0
Bank Sta=218.331,295.372
XS Rating Curve= 0 ,0
Exp/Cntr(USF)=0.3,0.1
Exp/Cntr=0.3,0.1

Type RM Length L Ch R = 1 ,1222.304,548.53,722.43,612.13
BEGIN DESCRIPTION:
Section 14
END DESCRIPTION:
XS GIS Cut Line= 6
311202.6582922785375318.08432861311080.0892295975375291.52023752
311001.2776659585375275.49598998 310930.410865625375283.56704749
310857.9901185185375301.84812405 310810.812773655375316.40013959
#Sta/Elev= 30
 103.411      10 118.205       8 168.887       6 203.279       4  223.53       2
 228.826    .987 230.167    .945 231.014    .051 234.209  -1.626 240.557  -1.716
 284.732   -.941 296.312       0 303.371    -.22 304.601    .111 306.346    .801
 457.938    .797  458.48    .009 462.679       0 470.477  -1.844 477.524  -2.709
 486.278   -1.65 490.799   -.694 491.932   -.045 493.932   1.955 494.909       2
 497.127       4 499.192       6 500.046   6.717 503.447       9 504.661      10
#Mann= 5 ,-1 , 0
 103.411     .07       0 231.014    .033       0 306.346    .033       0
 457.938    .033       0 491.932     .07       0
Bank Sta=231.014,491.932
XS Rating Curve= 0 ,0
Exp/Cntr(USF)=0.3,0.1
Exp/Cntr=0.3,0.1

Type RM Length L Ch R = 1 ,499.8937,567.66,442.59,442.59
BEGIN DESCRIPTION:
Section 12
END DESCRIPTION:
XS GIS Cut Line= 6
311337.5903698285374810.78114697 311249.457136755374747.68186726
311131.6691321285374738.43418147310760.5913682475374715.34974726
310666.6339756185374735.21120941310448.2327797425374889.53704158
#Sta/Elev= 30
 256.548       6 294.349   4.898 348.123       4 350.009   3.479 362.673       2
 363.525    1.43 484.282    .464 489.842    .057 490.797   -.653 547.048   -.666
 591.797   -.185 595.322    .346 962.822    .253 983.538   -.7741006.138   -.898
1009.636   -.6991011.383   -.0361014.768    .2591037.125    .057 1050.05      .6
1056.802   -.291  1069.1   -.6931147.125   -.1181198.843  -1.1391200.642   -.266
1201.919   -.065 1209.26       11211.108       21213.004   3.4611218.379       6
#Mann= 4 ,-1 , 0
 256.548     .07       0 363.525      .7       0 489.842    .033       0
1201.919     .07       0
Bank Sta=489.842,1201.919
XS Rating Curve= 0 ,0
Exp/Cntr(USF)=0.3,0.1
Exp/Cntr=0.3,0.1

Type RM Length L Ch R = 1 ,57.35342,568.02,1195.98,1195.98
BEGIN DESCRIPTION:
Section 11
END DESCRIPTION:
XS GIS Cut Line= 4
 311526.374036865373979.08673099311260.9337099525374083.20213892
310158.2408161745374511.06343219310038.4606327825374557.92244827
#Sta/Elev= 30
       0   5.736  91.859   4.858  105.23   3.257 285.129   1.749 285.781   1.047
 292.494    .126 308.073   -.947 339.918   -.404 435.096   -.369 463.695    .358
  483.44   -.604 660.111   -.377 732.918   -.856 791.717   -.564 792.521    .055
 812.436     .28 822.912   -.219 968.931   -.4511135.796    .2761138.349   -.581
1171.317   -.118 1304.72   -.1521379.722  -1.1791393.787  -2.1721402.468   -.988
1446.131   -.6151450.124    .0011454.862    .4331462.196    2.581596.541   3.661
#Mann= 5 ,-1 , 0
       0     .07       0 285.129     .07       0 292.494    .033       0
1450.124     .07       01462.196     .07       0
Bank Sta=292.494,1450.124
XS Rating Curve= 0 ,0
Exp/Cntr(USF)=0.3,0.1
Exp/Cntr=0.3,0.1

Type RM Length L Ch R = 1 ,10      ,5,5,5
BEGIN DESCRIPTION:
Section 10
END DESCRIPTION:
XS GIS Cut Line= 2
311456.4068745015373836.85237062309719.8104461875373026.24549711
#Sta/Elev= 30
       0   5.038  66.936   4.422  74.167   1.408  83.509   1.062  91.903   -.054
 121.143    -1.1 156.004  -1.084 190.858   -.328 362.679   -.403 374.825    .508
 535.255    .749 563.739    .609 581.983   -.651 721.814  -1.114 775.622   -.704
 796.897  -1.171 827.947    -.741276.104   -.5821311.633   -.1841316.223    .079
1317.875    .8941372.053    .6771421.634   1.5881430.526    .681 1459.68    .927
1495.693   -.4241694.807   -.2221792.923    .1891794.769    .9461916.468       4
#Mann= 3 , 0 , 0
       0     .07       0  91.903    .033       01694.807     .07       0
Bank Sta=91.903,1694.807
XS Rating Curve= 0 ,0
Exp/Cntr(USF)=0.3,0.1
Exp/Cntr=0.3,0.1

Storage Area=St. George's Riv,315276.371156,5374257.5283392
Storage Area Surface Line= 6
311385.5377275825373777.03734869
316340.9931740965376327.74331629
321661.3555116775374919.19745738
316282.6078535235374379.13324204
310279.8670817075371021.97730887
311385.5377275825373777.03734869
Storage Area Type= 0
Storage Area Area=30000
Storage Area Min Elev=-7
Storage Area Vol Elev= 1
               0

Chan Stop Cuts=-1
Use User Specified Reach Order=0
Composite Channel Slope=5

--- StephenvilleCrossi.g05 (geometry) ---

Geom Title=StephenvilleX, FrGIS, 17ext - Feb3,2011
Program Version=4.10

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